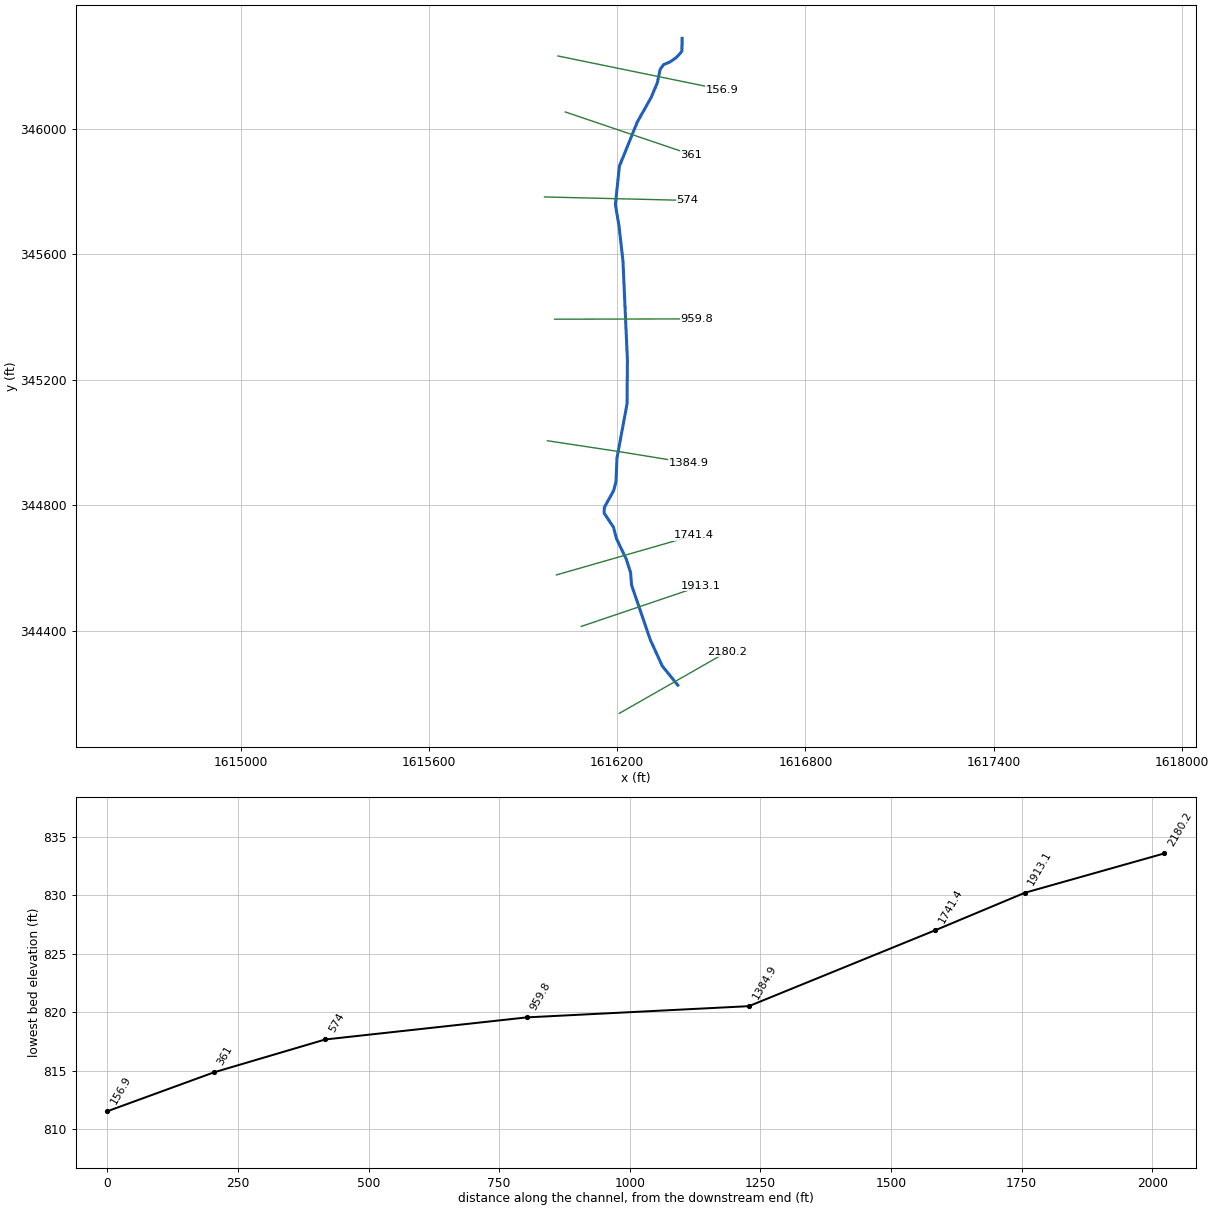
--- prttybrnch.prj (project) ---

Proj Title=prttybrnch
Current Plan=p01
Default Exp/Contr=0,0
English Units
Geom File=g01
Flow File=f01
Plan File=p01
BEGIN DESCRIPTION:
END DESCRIPTION:
DSS Export Rating Curves= 0
DSS Export Rating Curve Sorted= 0
DSS Export Volume Flow Curves= 0
DXF OffsetX= 0
DXF OffsetY= 0
DXF ScaleX= 0
DXF ScaleY= 0

--- prttybrnch.p01 (plan) ---

Plan Title=Approximate Study - 100yr
Program Version=4.00
Geom File=g01
Flow File=f01
Subcritical Flow
K Sum by GR= 0
Std Step Tol= 0.01
Critical Tol= 0.01
Num of Std Step Trials= 20
Max Error Tol= 0.3
Flow Tol Ratio= 0.001
Split Flow NTrial= 30
Split Flow Tol= 0.02
Split Flow Ratio= 0.02
Log Output Level= 0
Friction Slope Method= 1
Unsteady Friction Slope Method= 2
Unsteady Bridges Friction Slope Method= 1
Parabolic Critical Depth
Global Vel Dist= 0 , 0 , 0
Global Log Level= 0
CheckData=True
Encroach Param=-1 ,0,0, 0
Run HTab= 0
Run UNet= 0
Run PostProcess= 0
Run WQNet= 0
UNET Theta= 0
UNET Theta Warmup= 0
UNET ZTol= 0
UNET ZSATol= 0
UNET MxIter= 0
UNET MaxInSteps= 0
UNET DtIC= 0
UNET DtMin= 0
UNET MaxCRTS= 0
UNET WFStab= 0
UNET SFStab= 0
UNET WFX= 1
UNET SFX= 1
UNET DSS MLevel= 1
UNET DZMax Abort= 0
UNET Convert EG Bridges= 0
UNET Use Existing IB Tables= 0
UNET Froude Reduction=False
UNET Froude Limit= 0
UNET Froude Power= 0
UNET Time Slicing=0,0, 5
Write IC File= 0
Echo Input=False
Echo Output=False
Write Detailed= 0
Detailed Automatic Start=False, 0
WQ ULTIMATE=-1
WQ Max Comp Step=1HOUR
WQ Output Interval=15MIN
WQ Output Selected Increments= 0
WQ Output face flow=0
WQ Output face velocity=0
WQ Output face area=0
WQ Output face dispersion=0
WQ Output cell volume=0
WQ Output cell surface area=0
WQ Output cell continuity=0
WQ Output face conc=0
WQ Output face dconc_dx=0
WQ Output face courant=0
WQ Output face peclet=0
WQ Output face adv mass=0
WQ Output face disp mass=0
WQ Output cell mass=0
WQ Output cell source sink temp=0
WQ Output cell source sink nsm=0
WQ Output MaxMinRange=-1
WQ Daily Max Min Mean=-1
WQ Daily Range=0
WQ Daily Time=0
WQ Create Restart=0
WQ Fixed Restart=0
WQ System Summary=False
Sorting and Armoring Iterations= 10
XS Update Threshold= 0.02
Hydraulics Update Threshold= 0.02
Energy Slope Method= 1
Volume Change Method= 0
XS Weighting Method= 0
Number of US Weighted Cross Sections= 1
Number of DS Weighted Cross Sections= 1
Upstream XS Weight=0.25
Main XS Weight=0.5
Downstream XS Weight=0.25
Number of DS XS's Weighted with US Boundary= 1
Upstream Boundary Weight= 1
Weight of XSs Associated with US Boundary= 0
Number of US XS's Weighted with DS Boundary= 1
Downstream Boundary Weight= 0.5
Weight of XSs Associated with DS Boundary= 0.5
Sediment Output Level= 4
Mass or Volume Output= 0
Output Increment Type= 1
Profile and TS Output Increment= 10
XS Output Flag= 0
XS Output Increment= 10
Disregard all LS=0
Disregard all Conn=0
Disregard all Breaches=0
Disregard all Pumps=0

--- prttybrnch.f01 (steady flow) ---

Flow Title=USGS Regression Equation
Program Version=4.00
Number of Profiles= 1
Profile Names=P100yr
River Rch & RM=prttybrnch,Main            ,2180.2
     402
River Rch & RM=prttybrnch,Main            ,156.9
     432
Boundary for River Rch & Prof#=prttybrnch,Main            , 1
Up Type= 0
Dn Type= 3
Dn Slope=0.011474
DSS Import GetInterval= 0
DSS Import GetPeak= 0
DSS Import FillOption= 0

--- prttybrnch.g01 (geometry) ---

Geom Title=USGS 3m DEM
Program Version=4.00

River Reach=prttybrnch      ,Main
Reach XY= 30
     1616393.149      344226.348     1616343.491      344287.223
     1616305.239      344371.166     1616245.605      344545.286
     1616242.321      344585.926     1616228.524      344628.536
     1616197.329      344693.719     1616187.896      344730.045
     1616158.361       344774.45     1616158.133      344782.817
     1616158.851      344793.308      1616188.57      344847.187
     1616195.968      344876.576     1616198.976      344950.771
      1616231.08      345123.235     1616232.326      345261.798
     1616218.174      345578.213     1616205.586      345690.524
     1616193.934      345758.625     1616206.685      345881.352
     1616263.714       346021.92     1616308.317      346101.121
     1616327.784      346147.628     1616336.653      346189.634
     1616347.055      346204.881     1616368.301      346213.941
      1616387.33      346227.243     1616401.988      346242.617
     1616406.183      346249.094     1616406.638      346289.122

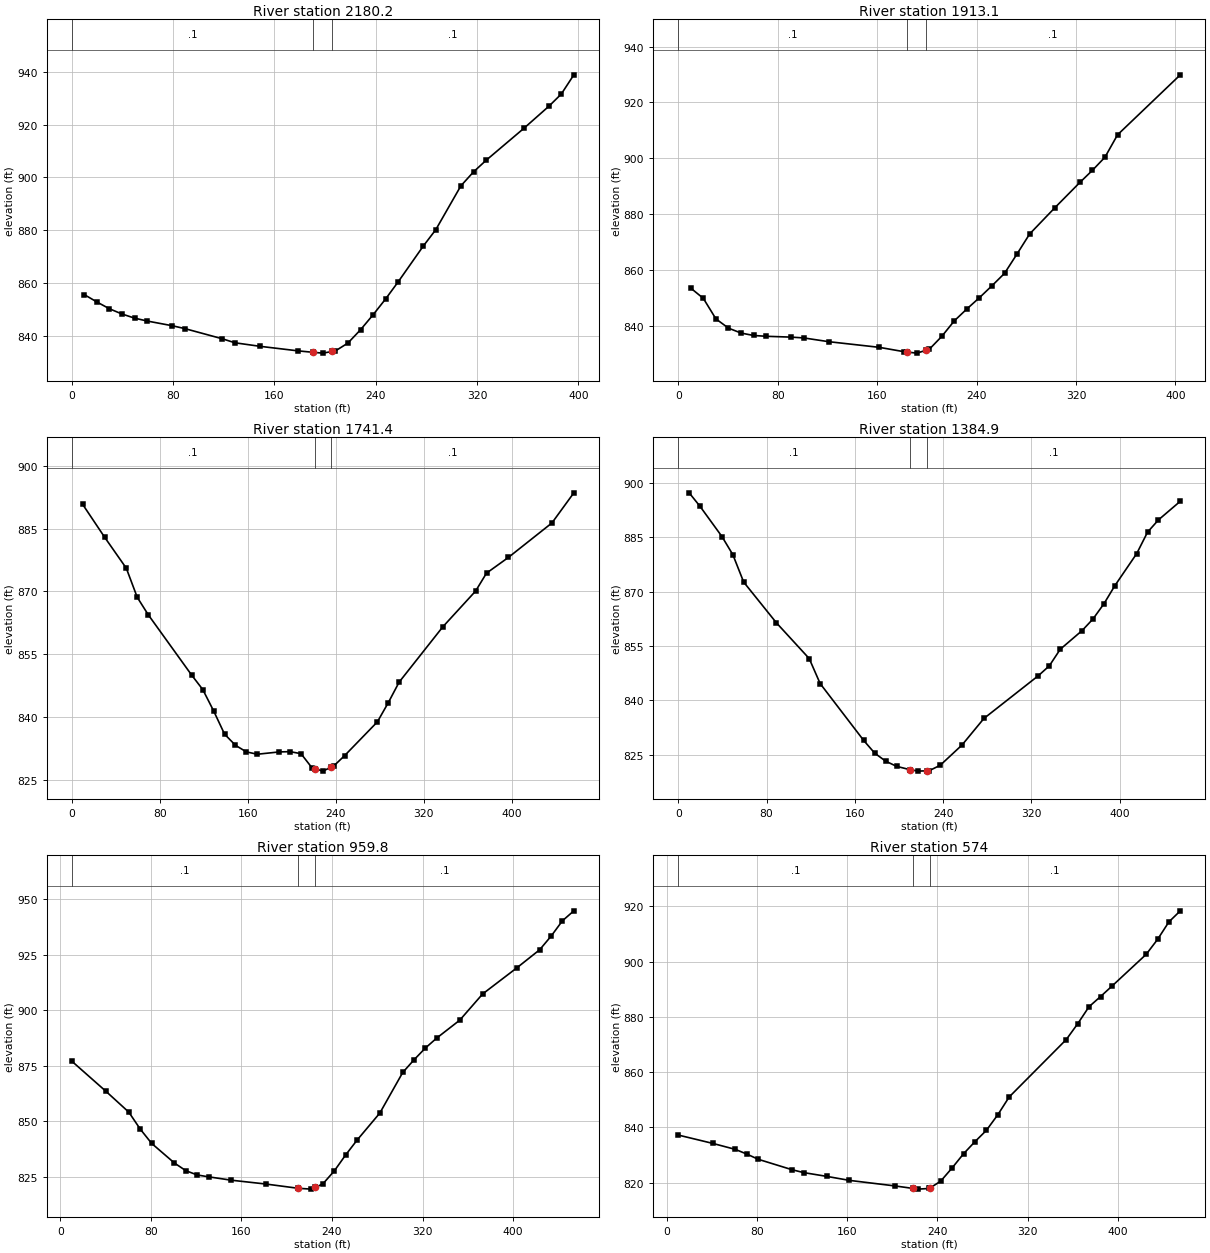
Type RM Length L Ch R = 1 ,2180.2  ,271.5,267.2,262.8
XS GIS Cut Line= 2
     1616206.419      344136.337     1616550.694      344332.914
#Sta/Elev= 30
     9.9  855.71    19.8  852.94    29.7  850.37    39.6  848.39    49.6  846.82
    59.5  845.73    79.3  843.95    89.2  842.87   118.9  839.01   128.8   837.5
   148.7  836.16   178.4  834.46   190.7  833.89   198.2  833.59   205.7  834.21
   208.1  834.41     218  837.39     228  842.43   237.9  848.09   247.8  854.08
   257.7  860.54   277.5  874.05   287.4  880.26   307.2  896.83   317.2  902.12
   327.1  906.48   356.8  918.52   376.6  926.89   386.5  931.55   396.4  938.81
#Mann= 3 , 0 , 0
       0      .1       0   190.7    .045       0   205.7      .1       0
Bank Sta=190.7,205.7
XS Rating Curve= 0 ,0
Exp/Cntr=0.3,0.1

Type RM Length L Ch R = 1 ,1913.1  ,172.8,171.7,170.6
XS GIS Cut Line= 2
     1616085.285       344413.67     1616467.813      344543.304
#Sta/Elev= 30
    10.1  853.49    20.2  849.82    30.3  842.49    40.4  839.17    50.5  837.41
    60.6  836.54    70.7  836.25    90.9  835.95     101  835.66   121.2  834.31
   161.6   832.3   181.8  830.72   184.4  830.59   191.9  830.22   199.4  831.23
   201.9  831.57     212  836.21   222.1  841.78   232.2  846.04   242.3  850.07
   252.4  854.35   262.5  858.79   272.6  865.76   282.7  872.88   302.9  882.24
   323.1  891.33   333.2  895.67   343.3  900.38   353.4  908.38   403.9  929.86
#Mann= 3 , 0 , 0
       0      .1       0   184.4    .045       0   199.4      .1       0
Bank Sta=184.4,199.4
XS Rating Curve= 0 ,0
Exp/Cntr=0.3,0.1

Type RM Length L Ch R = 1 ,1741.4  ,366.8,356.5,346
XS GIS Cut Line= 2
      1616005.88       344577.85     1616444.543      344703.806
#Sta/Elev= 30
     9.9   890.8    29.8  882.97    49.6  875.52    59.5  868.58    69.5  864.41
   109.1  849.93   119.1  846.51     129  841.39   138.9  835.85   148.8  833.19
   158.7  831.61   168.7  831.05   188.5   831.6   198.4  831.67   208.4  831.18
   218.3  827.82   220.7  827.62   228.2  827.01   235.7  827.94   238.1  828.23
     248  830.71   277.8  838.79   287.7  843.37   297.6   848.3   337.3  861.52
   367.1  870.07     377  874.35   396.9  878.11   436.5  886.36   456.4  893.56
#Mann= 3 , 0 , 0
       0      .1       0   220.7    .045       0   235.7      .1       0
Bank Sta=220.7,235.7
XS Rating Curve= 0 ,0
Exp/Cntr=0.3,0.1

Type RM Length L Ch R = 1 ,1384.9  ,421.6,425.1,428.7
XS GIS Cut Line= 3
     1615977.224      345005.809     1616202.152      344971.732
     1616426.736      344935.231
#Sta/Elev= 30
     9.9  897.27    19.8  893.52    39.6  885.22    49.5  880.21    59.3  872.66
      89  861.41   118.7  851.56   128.6  844.67   168.1  828.97     178  825.49
   187.9  823.28   197.8  821.85   210.1  820.91   217.6  820.52   225.1  820.62
   227.5  820.65   237.4  822.13   257.2  827.73     277  835.04   326.4  846.85
   336.3  849.56   346.2  854.13     366  859.28   375.9  862.49   385.8  866.68
   395.7  871.67   415.5  880.52   425.3  886.42   435.2  889.81     455  894.95
#Mann= 3 , 0 , 0
       0      .1       0   210.1    .045       0   225.1      .1       0
Bank Sta=210.1,225.1
XS Rating Curve= 0 ,0
Exp/Cntr=0.3,0.1

Type RM Length L Ch R = 1 ,959.8   ,386.5,385.8,385.2
XS GIS Cut Line= 2
     1616000.279      345393.365     1616453.999      345394.427
#Sta/Elev= 30
    10.1  877.16    40.3  863.58    60.5  854.21    70.6  846.57    80.7  840.13
   100.8  831.31   110.9  827.86     121  825.92   131.1  825.09   151.2  823.57
   181.5  821.86   210.3 819.925   221.8  819.56   225.3 820.367   231.9  821.89
     242  827.72   252.1  834.95   262.2  841.64   282.3  853.81   302.5  872.05
   312.6  877.82   322.6  883.09   332.7  887.61   352.9   895.6   373.1  907.39
   403.3  919.13   423.5  927.29   433.6  933.41   443.6  940.32   453.7  944.81
#Mann= 3 , 0 , 0
    10.1      .1       0   210.3    .045       0   225.3      .1       0
Bank Sta=210.3,225.3
XS Rating Curve= 0 ,0
Exp/Cntr=0.3,0.1

Type RM Length L Ch R = 1 ,574     ,219.8,212.9,206.1
XS GIS Cut Line= 2
     1615967.848      345783.298     1616423.236       345772.26
#Sta/Elev= 30
    10.1  837.23    40.5  834.23    60.7  832.05    70.9  830.36      81  828.47
   111.3  824.66   121.5  823.64   141.7  822.29     162  820.83   202.5  818.82
   218.2 817.934   222.7  817.67   232.8  817.91   233.2 818.014   242.9  820.54
   253.1  825.35   263.2  830.46   273.3  834.83   283.4   838.9   293.6  844.57
   303.7  851.01   354.3  871.76   364.4  877.44   374.5  883.64   384.7  887.31
   394.8  891.07   425.2  902.58   435.3  907.98   445.4  914.34   455.5  918.33
#Mann= 3 , 0 , 0
    10.1      .1       0   218.2    .045       0   233.2      .1       0
Bank Sta=218.2,233.2
XS Rating Curve= 0 ,0
Exp/Cntr=0.3,0.1

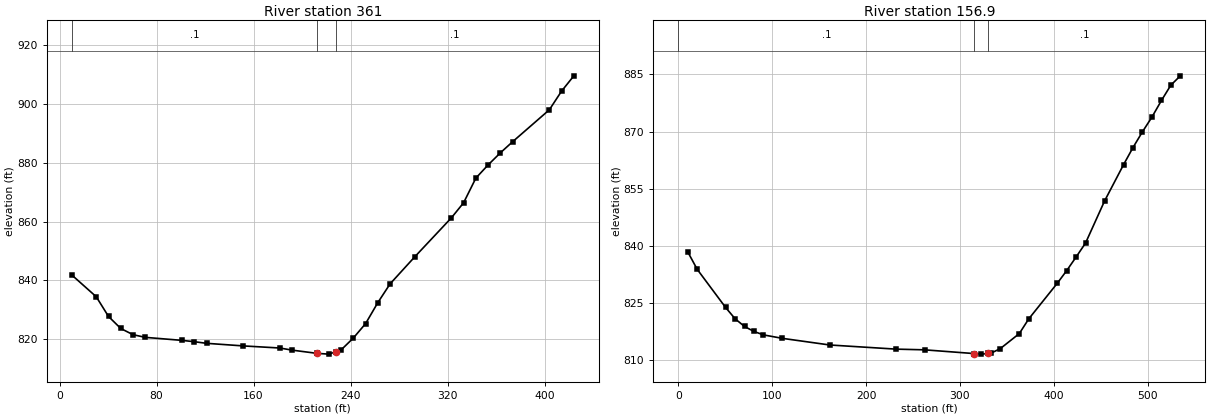
Type RM Length L Ch R = 1 ,361     ,201.3,204.2,207
XS GIS Cut Line= 2
     1616034.282      346054.287     1616435.935      345918.277
#Sta/Elev= 30
    10.1  841.81    30.3  834.39    40.4  827.68    50.5  823.59    60.6  821.48
    70.7  820.57     101  819.54   111.1  819.09   121.2  818.54   151.4  817.66
   181.7  816.94   191.8  816.22   212.6 815.106   222.1  814.86   227.6 815.645
   232.2   816.3   242.3  820.35   252.4  825.26   262.5  832.42   272.6  838.79
   292.8  847.93   323.1  861.25   333.2  866.39   343.3  874.78   353.4  879.27
   363.5  883.38   373.6  887.16   403.9  898.04     414   904.4   424.1   909.6
#Mann= 3 , 0 , 0
    10.1      .1       0   212.6    .045       0   227.6      .1       0
Bank Sta=212.6,227.6
XS Rating Curve= 0 ,0
Exp/Cntr=0.3,0.1

Type RM Length L Ch R = 1 ,156.9   ,152.6,156.9,161.1
XS GIS Cut Line= 2
     1616010.905        346232.8     1616534.755      346125.479
#Sta/Elev= 30
    10.1  838.41    20.2   833.8    50.4   823.8    60.5  820.83    70.6  818.79
    80.7  817.48    90.8  816.58     111  815.67   161.4  813.93   232.1  812.84
   262.3  812.66   315.4  811.67   322.9  811.53   330.4   811.7   332.9  811.76
     343  812.98   363.2  816.92   373.3  820.79   403.6  830.12   413.7  833.47
   423.7  837.03   433.8  840.72     454  851.74   474.2  861.27   484.3  865.79
   494.4  869.94   504.5   873.8   514.6  878.15   524.6  882.17   534.7  884.63
#Mann= 3 , 0 , 0
       0      .1       0   315.4    .045       0   330.4      .1       0
Bank Sta=315.4,330.4
XS Rating Curve= 0 ,0
Exp/Cntr=0.3,0.1

Chan Stop Cuts=-1
Use User Specified Reach Order=0